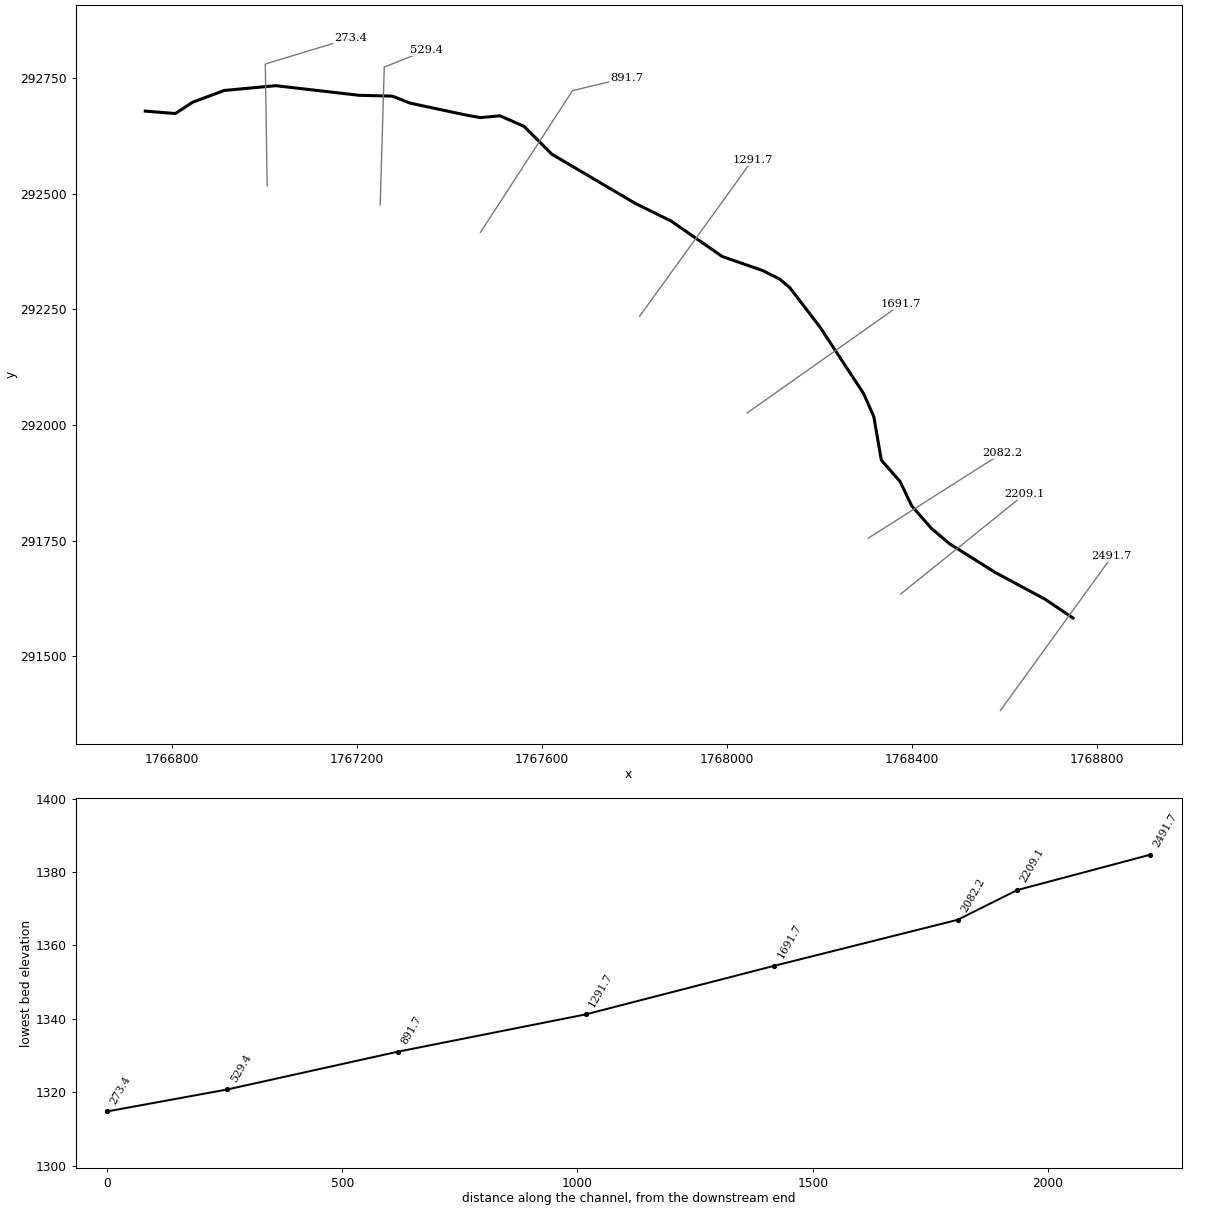
--- ELKCKBRNCH.prj (project) ---

Proj Title=ELKCKBRNCH
Current Plan=p01
Geom File=g01
Flow File=f01
Plan File=p01
DSS Export Rating Curves=0
DSS Export Rating Curve Sorted=0
DSS Export Volume Flow Curves=0
DXF OffsetX=0
DXF OffsetY=0
DXF ScaleX=0
DXF ScaleY=0

--- ELKCKBRNCH.p01 (plan) ---

Plan Title=Floodplain
Program Version=4.00
Geom File=g01
Flow File=f01
K Sum by GR=0
Std Step Tol=0.01
Critical Tol=0.01
Num of Std Step Trials=20
Max Error Tol=0.3
Flow Tol Ratio=0.001
Split Flow NTrial=30
Split Flow Tol=0.02
Split Flow Ratio=0.02
Log Output Level=0
Friction Slope Method=1
Unsteady Friction Slope Method=2
Unsteady Bridges Friction Slope Method=1
Global Log Level=0
CheckData=False
Run HTab=0
Run UNet=0
Run PostProcess=0
UNET Theta=0
UNET Theta Warmup=0
UNET ZTol=0
UNET ZSATol=0
UNET MxIter=0
UNET MaxInSteps=0
UNET DtIC=0
UNET DtMin=0
UNET MaxCRTS=0
UNET WFStab=0
UNET SFStab=0
UNET WFX=0
UNET SFX=0
UNET DSS MLevel=0
UNET DZMax Abort=0
UNET Convert EG Bridges=0
UNET Use Existing IB Tables=0
UNET Froude Limit=0
UNET Froude Power=0
Write IC File=0
Echo Input=False
Echo Output=False
Write Detailed=0

--- ELKCKBRNCH.f01 (steady flow) ---

Flow Title=NFF Regression Equation
Program Version=4.00
Number of Profiles=1
Profile Names=P100yr
River Rch & RM=ELKCKBRNCH,Main      ,2491.7
879.6814
River Rch & RM=ELKCKBRNCH,Main      ,529.4
915.4482
Boundary for River Rch & Prof#=ELKCKBRNCH,Main      ,1
Up Type=0
Dn Type=3
Dn Slope=0.026367

--- ELKCKBRNCH.g01 (geometry) ---

Geom Title=USGS 10m DEM
Program Version=4.00

River Reach=ELKCKBRNCH     ,Main
Reach XY= 30
     1768749.092      291582.582     1768688.866      291623.118
     1768581.153      291681.029     1768481.548      291743.572
     1768443.327      291776.001     1768400.473      291824.646
     1768374.993      291877.923     1768334.456      291924.251
     1768318.241      292018.066     1768296.235      292067.869
     1768201.262      292212.644     1768136.403      292297.193
     1768114.397      292315.724     1768077.334      292334.256
     1767990.469      292364.369     1767880.440      292440.810
     1767802.841      292479.031     1767622.161      292585.585
     1767561.934      292645.812     1767509.959      292668.666
     1767467.735      292664.825     1767439.666      292669.637
     1767315.364      292696.101     1767276.998      292711.271
     1767205.208      292712.988     1767024.528      292733.835
     1766913.340      292723.412     1766845.007      292697.931
     1766807.944      292673.609     1766742.744      292678.793

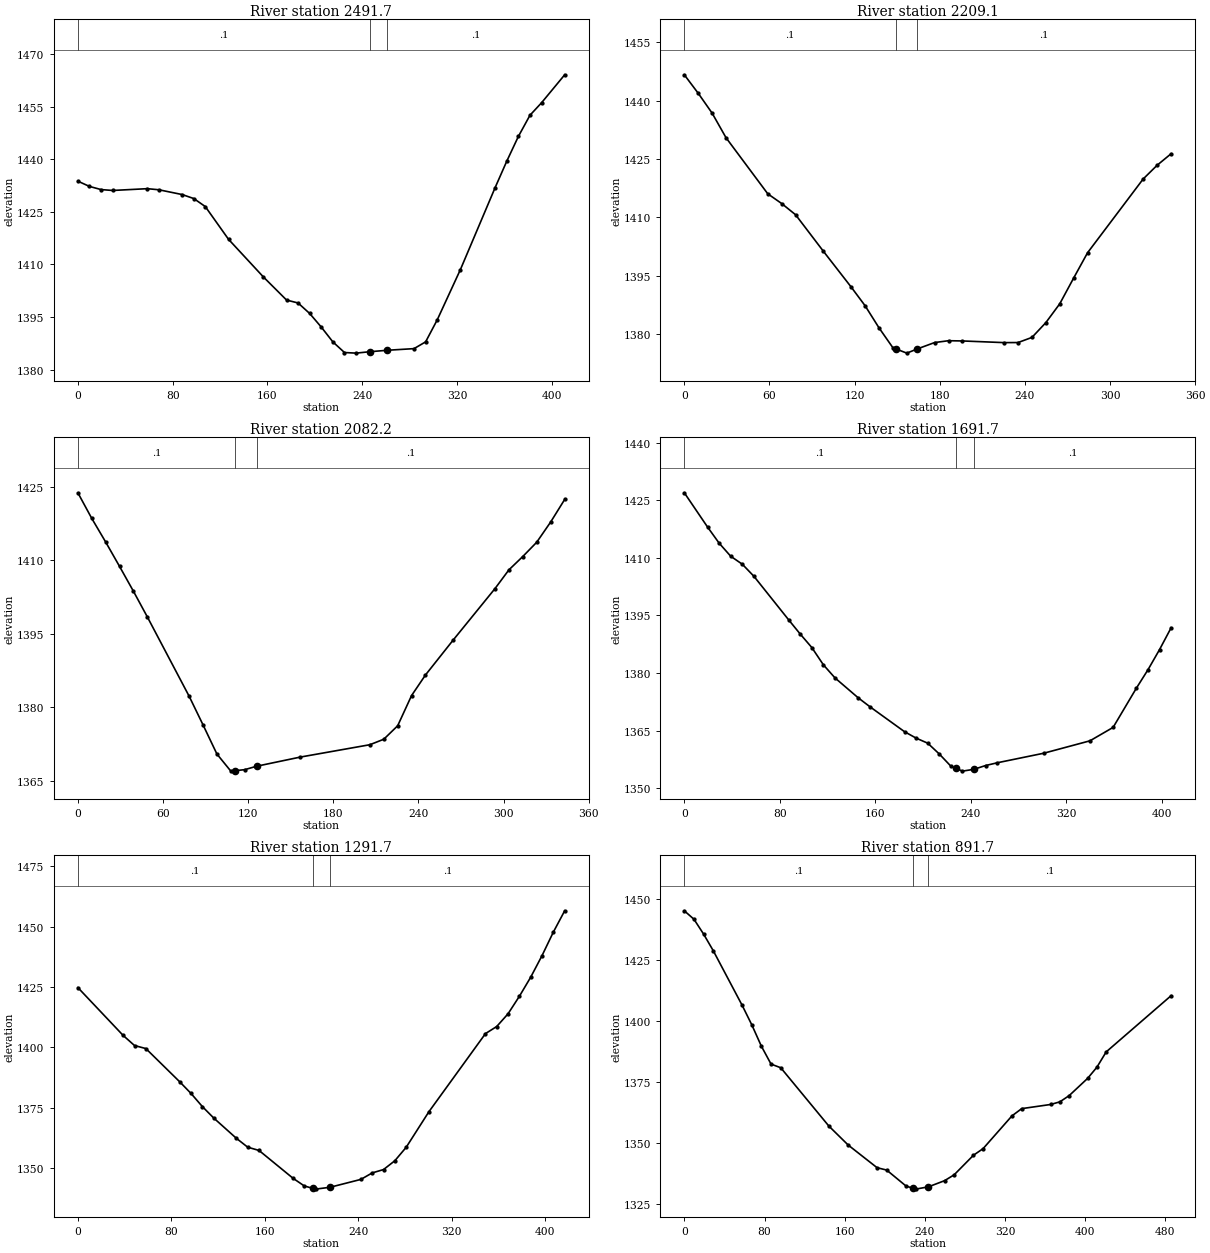
Type RM Length L Ch R = 1 ,2491.7,288.8,282.5,276.2
XS GIS Cut Line= 2
     1768592.092      291382.824     1768833.167      291715.734
#Sta/Elev= 30
       0 1433.74     9.8 1432.24    19.6 1431.34    29.4 1431.09    58.7 1431.60
    68.5 1431.28    88.1 1429.92    97.9 1428.78   107.6 1426.49   127.2 1417.16
   156.6 1406.44   176.2 1399.84   185.9 1399.01   195.7 1396.02   205.5 1392.14
   215.3 1387.91   225.1 1384.88   234.9 1384.71   246.4 1385.11   261.4 1385.53
   283.8 1385.99   293.6 1387.92   303.4 1394.19   323.0 1408.55   352.3 1431.91
   362.1 1439.42   371.9 1446.48   381.7 1452.53   391.5 1456.10   411.0 1464.06
#Mann= 3 , 0 , 0
       0     0.1       0   246.4   0.045       0   261.4     0.1       0
Bank Sta=   246.4,   261.4
Exp/Cntr=0.3,0.1

Type RM Length L Ch R = 1 ,2209.1,129.2,126.9,124.6
XS GIS Cut Line= 2
     1768376.468      291634.675     1768643.667      291849.832
#Sta/Elev= 28
       0 1446.61     9.8 1441.86    19.6 1436.75    29.4 1430.43    58.8 1416.03
    68.6 1413.53    78.4 1410.65    98.0 1401.26   117.6 1392.06   127.4 1387.26
   137.2 1381.58   147.0 1376.46   149.2 1376.15   156.8 1375.08   164.2 1376.16
   176.4 1377.80   186.2 1378.27   196.0 1378.21   225.4 1377.78   235.2 1377.80
   245.0 1379.12   254.8 1382.92   264.6 1387.76   274.4 1394.38   284.2 1400.88
   323.4 1419.84   333.3 1423.39   343.1 1426.33
#Mann= 3 , 0 , 0
       0     0.1       0   149.2   0.045       0   164.2     0.1       0
Bank Sta=   149.2,   164.2
Exp/Cntr=0.3,0.1

Type RM Length L Ch R = 1 ,2082.2,389.4,390.4,391.4
XS GIS Cut Line= 2
     1768306.228      291755.267     1768595.777      291939.250
#Sta/Elev= 26
       0 1423.79     9.8 1418.56    19.6 1413.74    29.4 1408.75    39.2 1403.67
    49.0 1398.43    78.4 1382.27    88.2 1376.42    98.0 1370.46   107.8 1366.97
     111 1367.07   117.6 1367.27     126 1367.97   156.8 1369.84   205.8 1372.36
   215.6 1373.48   225.4 1376.23   235.2 1382.40   245.0 1386.60   264.6 1393.76
   294.0 1404.24   303.8 1408.06   313.6 1410.79   323.4 1413.70   333.3 1417.86
   343.1 1422.43
#Mann= 3 , 0 , 0
       0     0.1       0     111   0.045       0     126     0.1       0
Bank Sta=     111,     126
Exp/Cntr=0.3,0.1

Type RM Length L Ch R = 1 ,1691.7,392.4,399.9,407.3
XS GIS Cut Line= 2
     1768044.138      292025.927     1768377.219      292261.184
#Sta/Elev= 30
       0 1426.96    19.4 1418.06    29.1 1413.86    38.8 1410.44    48.6 1408.34
    58.3 1405.20    87.4 1393.85    97.1 1390.14   106.8 1386.63   116.5 1382.12
   126.2 1378.72   145.6 1373.54   155.4 1371.22   184.5 1364.69   194.2 1363.02
   203.9 1361.70   213.6 1358.88   223.3 1355.70   227.5 1355.15   233.0 1354.42
   242.5 1354.89   252.4 1355.88   262.2 1356.60   301.0 1359.08   339.8 1362.32
   359.2 1365.82   378.7 1376.05   388.4 1380.84   398.1 1386.10   407.8 1391.79
#Mann= 3 , 0 , 0
       0     0.1       0   227.5   0.045       0   242.5     0.1       0
Bank Sta=   227.5,   242.5
Exp/Cntr=0.3,0.1

Type RM Length L Ch R = 1 ,1291.7,398.7,399.9,401.1
XS GIS Cut Line= 2
     1767811.774      292235.054     1768055.725      292572.999
#Sta/Elev= 30
       0 1424.75    38.8 1404.90    48.5 1400.73    58.2 1399.48    87.2 1385.70
    96.9 1380.86   106.6 1375.42   116.3 1370.69   135.7 1362.28   145.4 1358.60
   155.1 1357.24   184.2 1345.72   193.9 1342.51     201 1341.56   203.6 1341.21
     216 1341.99   242.3 1345.24   252.0 1347.93   261.7 1349.32   271.4 1352.98
   281.1 1358.55   300.5 1373.25   349.0 1405.68   358.6 1408.61   368.3 1413.87
   378.0 1421.12   387.7 1429.04   397.4 1437.98   407.1 1447.74   416.8 1456.57
#Mann= 3 , 0 , 0
       0     0.1       0     201   0.045       0     216     0.1       0
Bank Sta=     201,     216
Exp/Cntr=0.3,0.1

Type RM Length L Ch R = 1 ,891.7,349.2,361.7,374.2
XS GIS Cut Line= 3
     1767467.615      292416.615     1767666.661      292723.041
     1767783.642      292751.189
#Sta/Elev= 30
       0 1445.29     9.6 1441.83    19.2 1435.75    28.8 1428.95    57.7 1406.48
    67.3 1398.48    76.9 1389.68    86.5 1382.37    96.2 1380.86   144.2 1356.92
   163.5 1349.12   192.3 1339.83   201.9 1338.85   221.2 1332.30   228.5 1331.33
   230.8 1331.03   243.5 1331.97   259.6 1334.49   269.2 1336.91   288.5 1344.95
   298.1 1347.66   326.9 1361.11   336.6 1364.08   365.4 1365.78   374.6 1366.85
   383.9 1369.40   402.4 1376.51   411.7 1381.12   420.9 1387.37   485.7 1410.46
#Mann= 3 , 0 , 0
       0     0.1       0   228.5   0.045       0   243.5     0.1       0
Bank Sta=   228.5,   243.5
Exp/Cntr=0.3,0.1

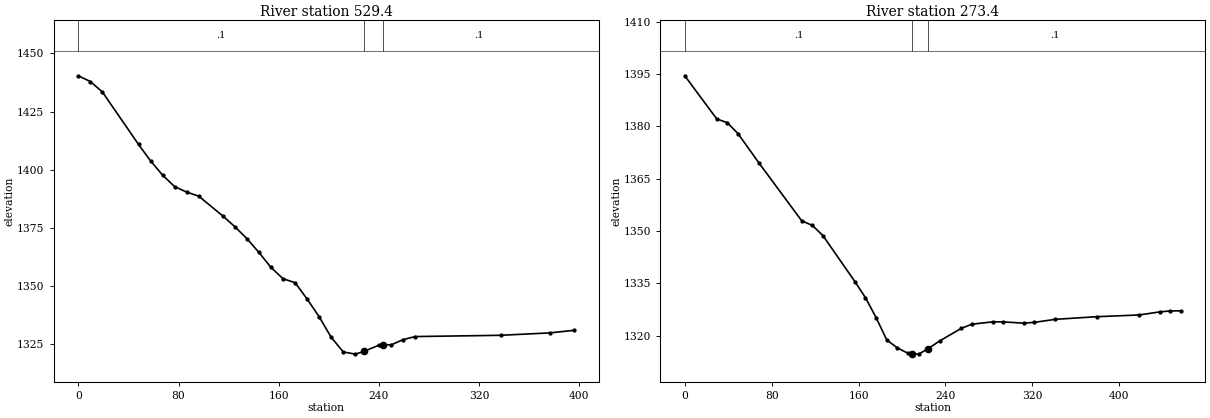
Type RM Length L Ch R = 1 ,529.4,254.9,255.9,256.9
XS GIS Cut Line= 3
     1767250.808      292476.075     1767259.571      292774.034
     1767350.496      292810.254
#Sta/Elev= 30
       0 1440.36     9.6 1437.92    19.2 1433.43    48.1 1410.87    57.7 1403.81
    67.3 1397.68    76.9 1392.76    86.5 1390.40    96.2 1388.64   115.4 1380.13
   125.0 1375.53   134.6 1370.42   144.2 1364.49   153.8 1358.06   163.5 1353.15
   173.1 1351.48   182.7 1344.46   192.3 1336.85   201.9 1328.03   211.6 1321.70
   221.2 1320.76   228.1 1321.92   240.4 1324.68   243.1 1324.71   250.0 1324.79
   259.6 1327.04   269.2 1328.31   337.2 1328.85   376.4 1329.88   396.0 1331.00
#Mann= 3 , 0 , 0
       0     0.1       0   228.1   0.045       0   243.1     0.1       0
Bank Sta=   228.1,   243.1
Exp/Cntr=0.3,0.1

Type RM Length L Ch R = 1 ,273.4,276.4,273.1,269.8
XS GIS Cut Line= 3
     1767006.358      292516.454     1767002.374      292780.717
     1767186.426      292836.506
#Sta/Elev= 30
       0 1394.51    29.4 1382.17    39.2 1381.07    48.9 1377.98    68.5 1369.45
   107.7 1352.95   117.5 1351.65   127.2 1348.72   156.6 1335.57   166.4 1330.92
   176.2 1325.20   186.0 1318.82   195.8 1316.53   205.6 1315.00   209.3 1314.91
   215.4 1314.76   224.3 1316.37   234.9 1318.58   254.5 1322.12   264.3 1323.33
   283.5 1324.01   293.1 1324.00   312.4 1323.63   322.0 1323.87   341.2 1324.73
   379.7 1325.49   418.2 1325.98   437.4 1326.86   447.0 1327.14   456.6 1327.17
#Mann= 3 , 0 , 0
       0     0.1       0   209.3   0.045       0   224.3     0.1       0
Bank Sta=   209.3,   224.3
Exp/Cntr=0.3,0.1